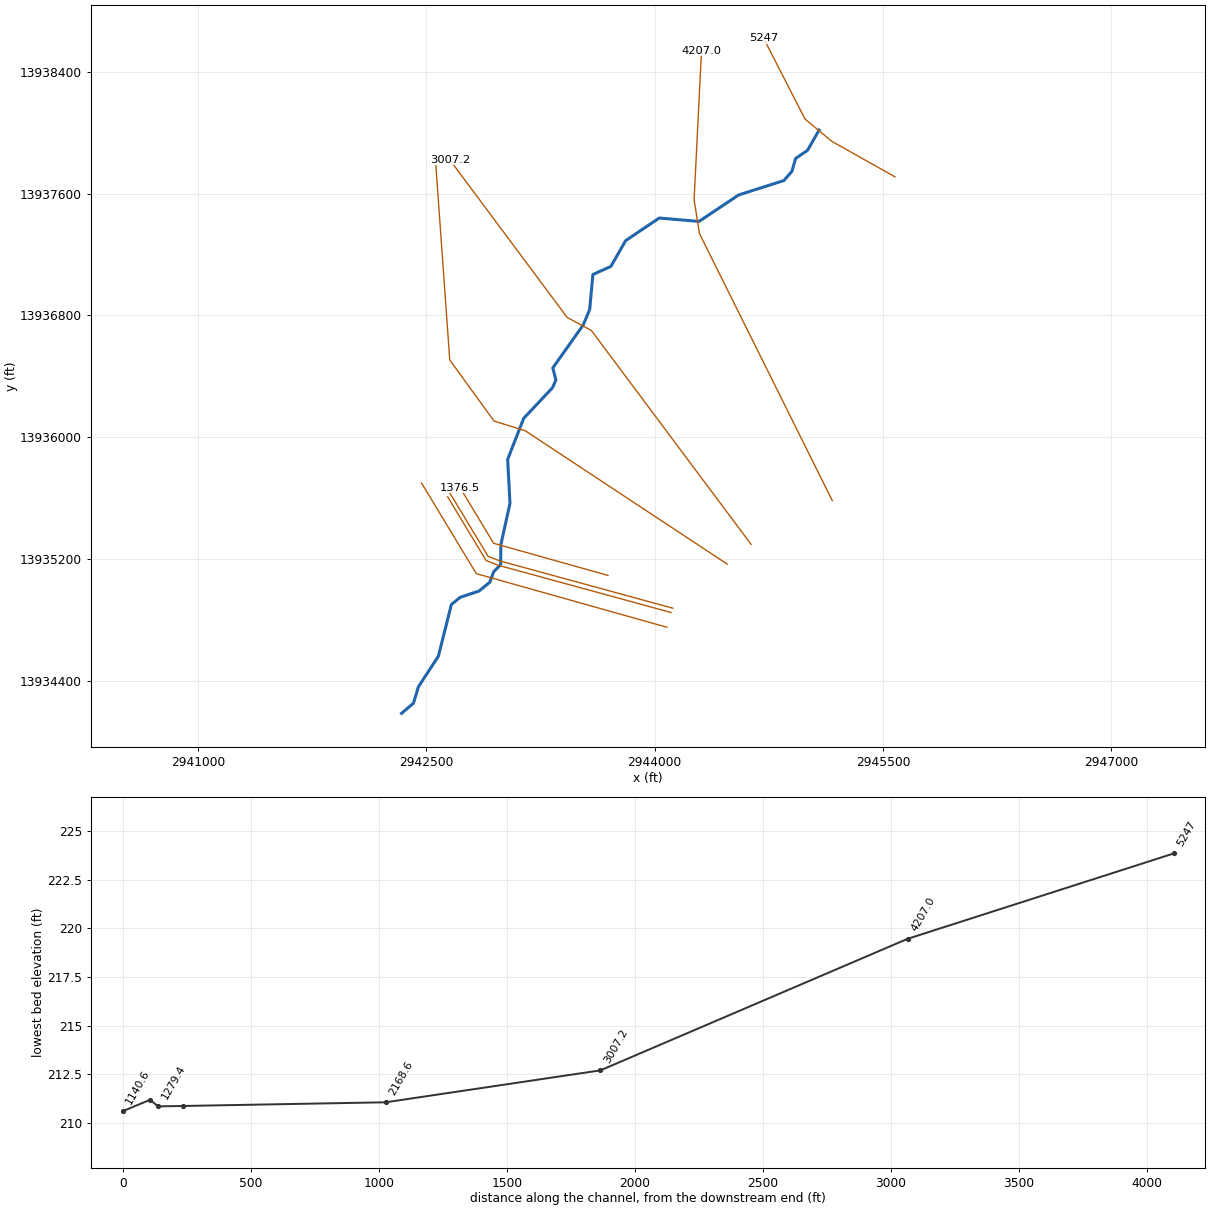
--- K166-03-00.prj (project) ---

Proj Title=K166-03-00
Current Plan=p02
Default Exp/Contr=.3,.1
English Units
Geom File=g01
Flow File=f01
Flow File=f04
Flow File=f02
Plan File=p01
Plan File=p04
Plan File=p02
Y Axis Title=Elevation
X Axis Title(PF)=Main Channel Distance
X Axis Title(XS)=Station
BEGIN DESCRIPTION:
Cypress Creek Watershed
Mound Creek Tributary 7.62
HCFCD Unit K166-03-00
Flood Hazard Model
10, 2, 1, 0.2%
Filename K166-03-00
Prepared by:  Halff Associates Inc  DATE:  March 24, 2004
Reviewed by:  _________  DATE:  __________________
STATUS (Final)
END DESCRIPTION:
DSS Export Rating Curves= 0
DSS Export Rating Curve Sorted= 0
DSS Export Volume Flow Curves= 0
DXF OffsetX= 0
DXF OffsetY= 0
DXF ScaleX= 1
DXF ScaleY= 10

--- K166-03-00.p02 (plan) ---

Plan Title=Floodway
Version=Version 3.0.1  Mar 2001
Short Identifier=Floodway0607
Geom File=g01
Flow File=f02
Subcritical Flow
K Sum by GR= 0
Std Step Tol= 0.01
Critical Tol= 0.01
Num of Std Step Trials= 20
Max Error Tol= 0.3
Flow Tol Ratio= 0.001
Split Flow NTrial= 30
Split Flow Tol= 0.02
Split Flow Ratio= 0.02
Log Output Level= 0
Friction Slope Method= 1
Unsteady Friction Slope Method= 2
Parabolic Critical Depth
Global Vel Dist= 0 , 0 , 0
Global Log Level= 0
CheckData=True
Encroach Param=-1 ,0,0, 3
Encroach River=K166-03-00
Encroach Reach=Reach - 1
Encroach Node=5247
       1  4934.4 5083.44       1  4934.4 5083.44
Encroach Node=4207.0
       1 4989.64 5219.14       1 4989.64 5219.14
Encroach Node=3007.2
       1 4803.46 5060.28       1 4803.46 5060.28
Encroach Node=2168.6
       1 4852.39 5055.42       1 4852.39 5055.42
Encroach Node=1376.5
       1  4842.5 5146.09       0       0       0
Encroach Node=1279.4
       1  4842.5 5146.09       1  4872.5 5116.09
Encroach Node=1252.3
       1  4842.5 5146.09       1  4872.5 5116.09
Encroach Node=1248.6
       1  4842.5 5146.09       1  4872.5 5116.09
Encroach Node=1140.6
       1  4842.5 5146.09       0       0       0
Encroach Reach=K166-03-00_0011
Encroach Node=5247
       1  4934.4 5083.44       0       0       0
Encroach Node=4207.0
       1 4989.64 5219.14       0       0       0
Encroach Node=3007.2
       1 4803.46 5060.28       0       0       0
Encroach Node=2168.6
       1 4852.39 5055.42       0       0       0
Encroach Node=1376.5
       1  4842.5 5146.09       0       0       0
Encroach Node=1279.4
       1  4842.5 5146.09       0       0       0
Encroach Node=1252.3
       1  4842.5 5146.09       0       0       0
Encroach Node=1248.6
       1  4842.5 5146.09       0       0       0
Encroach Node=1140.6
       1  4842.5 5146.09       0       0       0
Computation Interval=1HOUR
Output Interval=1HOUR
Run HTab= 0
Run UNet= 0
Run PostProcess= 0
UNET Theta= 1
UNET ZTol= 0.02
UNET ZSATol= 0.1
UNET MxIter= 20
UNET MaxInSteps= 20
UNET DtIC= 0
UNET DtMin= 0
UNET MaxCRTS= 20
UNET WFStab= 2
UNET SFStab= 1
UNET WFX= 1
UNET SFX= 1
UNET Convert EG Bridges=-1
UNET Use Existing IB Tables=-1
Instantaneous Interval=1HOUR
Write IC File= 0
Write Velocity= 0
Write Detailed= 0

--- K166-03-00.p01 (plan) ---

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Plan Title=FEMA Effective June 2007
Program Version=3.13
Short Identifier=FEMAeff0607
Geom File=g01
Flow File=f01
Unsteady Bridges Friction Slope Method= 1
Encroach Param=-1 ,0,0, 0
UNET Theta Warmup= 1
UNET DSS MLevel= 4
UNET DZMax Abort= 100
UNET Froude Reduction=False
UNET Froude Limit= 1
UNET Froude Power= 10
IC Time=0,,
Echo Input=False
Echo Output=False
Detailed Automatic Start=False, 10

--- K166-03-00.p04 (plan) ---

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Plan Title=Storage Routing
Short Identifier=Store_Rout
Geom File=g01
Flow File=f04
Encroach Param=-1 ,0,0, 0

--- K166-03-00.f02 (steady flow) ---

Flow Title=Floodway
Version=Version 3.0.1  Mar 2001
Number of Profiles= 2
Profile Names=1PCT_100yr, 1PCTFloodway_100yrFW
River Rch & RM=K166-03-00,K166-03-00_0011,5247
    2080    2080
River Rch & RM=K166-03-00,K166-03-00_0011,3007.2
    2350    2350
River Rch & RM=K166-03-00,K166-03-00_0011,2168.6
    2390    2390
River Rch & RM=K166-03-00,K166-03-00_0011,1279.4
    2443    2443
Boundary for River Rch & Prof#=K166-03-00,K166-03-00_0011, 1
Up Type= 0
Dn Type= 3
Dn Slope=.0052
Boundary for River Rch & Prof#=K166-03-00,K166-03-00_0011, 2
Up Type= 0
Dn Type= 1
Dn Known WS=217.88
DSS Import GetInterval= 0
DSS Import GetPeak= 0
DSS Import FillOption= 0

--- K166-03-00.f01 (steady flow) ---

Flow Title=FEMA Effective June 2007
Version=Version 3.0.1  Mar 2001
Number of Profiles= 4
Profile Names=10PCT_10yr, 2PCT_50yr, 1PCT_100yr, 0.2PCT_500yr
River Rch & RM=K166-03-00,K166-03-00_0011,5247
    1170    1800    2080    2940
River Rch & RM=K166-03-00,K166-03-00_0011,3007.2
    1300    2000    2350    3300
River Rch & RM=K166-03-00,K166-03-00_0011,2168.6
    1340    2050    2390    3350
River Rch & RM=K166-03-00,K166-03-00_0011,1279.4
    1406    2116    2443    3429
Boundary for River Rch & Prof#=K166-03-00,K166-03-00_0011, 1
Up Type= 0
Dn Type= 3
Dn Slope=.0052
Boundary for River Rch & Prof#=K166-03-00,K166-03-00_0011, 2
Up Type= 0
Dn Type= 3
Dn Slope=.0052
Boundary for River Rch & Prof#=K166-03-00,K166-03-00_0011, 3
Up Type= 0
Dn Type= 3
Dn Slope=.0052
Boundary for River Rch & Prof#=K166-03-00,K166-03-00_0011, 4
Up Type= 0
Dn Type= 3
Dn Slope=.0052
DSS Import GetInterval= 0
DSS Import GetPeak= 0
DSS Import FillOption= 0

--- K166-03-00.f04 (steady flow) ---

Flow Title=Storage Routing
Version=Version 3.0.1  Mar 2001
Number of Profiles= 7
Profile Names=0.25*10% flood, 0.50*10%flood, 10% flood, 2% flood, 1% flood, 0.2%flood, 1.25*0.2% flood
River Rch & RM=K166-03-00,K166-03-00_0011,5247
      55     110     220     410     490     590     738
River Rch & RM=K166-03-00,K166-03-00_0011,4207
      55     110     220     410     490     590     738
River Rch & RM=K166-03-00,K166-03-00_0011,3007.2
      68     135     270     490     600     730     913
River Rch & RM=K166-03-00,K166-03-00_0011,2168.6
      93     185     370     650     800     980    1225
River Rch & RM=K166-03-00,K166-03-00_0011,1279.4
     115     230     460     800    1010    1240    1550
Boundary for River Rch & Prof#=K166-03-00,K166-03-00_0011, 1
Up Type= 0
Dn Type= 3
Dn Slope=.0052
Boundary for River Rch & Prof#=K166-03-00,K166-03-00_0011, 2
Up Type= 0
Dn Type= 3
Dn Slope=.0052
Boundary for River Rch & Prof#=K166-03-00,K166-03-00_0011, 3
Up Type= 0
Dn Type= 3
Dn Slope=.0052
Boundary for River Rch & Prof#=K166-03-00,K166-03-00_0011, 4
Up Type= 0
Dn Type= 3
Dn Slope=.0052
Boundary for River Rch & Prof#=K166-03-00,K166-03-00_0011, 5
Up Type= 0
Dn Type= 3
Dn Slope=.0052
Boundary for River Rch & Prof#=K166-03-00,K166-03-00_0011, 6
Up Type= 0
Dn Type= 3
Dn Slope=.0052
Boundary for River Rch & Prof#=K166-03-00,K166-03-00_0011, 7
Up Type= 0
Dn Type= 3
Dn Slope=.0052
DSS Import GetInterval= 0
DSS Import GetPeak= 0
DSS Import FillOption= 0

--- K166-03-00.g01 (geometry) ---

Geom Title=K166-03-00 June 2007
Version=Version 3.0.1  Mar 2001

River Reach=K166-03-00      ,K166-03-00_0011
Reach XY= 30
      2945080.27      13938016.7       2945003.5      13937883.2
      2944925.73     13937830.22      2944901.89     13937745.92
      2944848.69     13937685.33      2944551.32     13937590.34
      2944291.59      13937416.7      2944030.34     13937439.13
      2943809.41      13937290.7      2943712.55     13937121.34
      2943594.42     13937068.18      2943573.15     13936837.82
      2943530.35     13936736.05      2943331.14     13936454.79
      2943351.06     13936374.72      2943328.61     13936323.92
      2943139.59     13936123.09      2943034.45     13935853.74
      2943049.81     13935565.49      2942990.04     13935294.11
      2942988.16     13935162.28      2942942.39      13935115.1
      2942916.95     13935046.71      2942846.62     13934988.99
      2942722.57     13934947.64      2942664.69     13934900.38
      2942579.63     13934561.33      2942448.42     13934360.36
      2942415.42     13934251.82      2942337.29      13934185.4

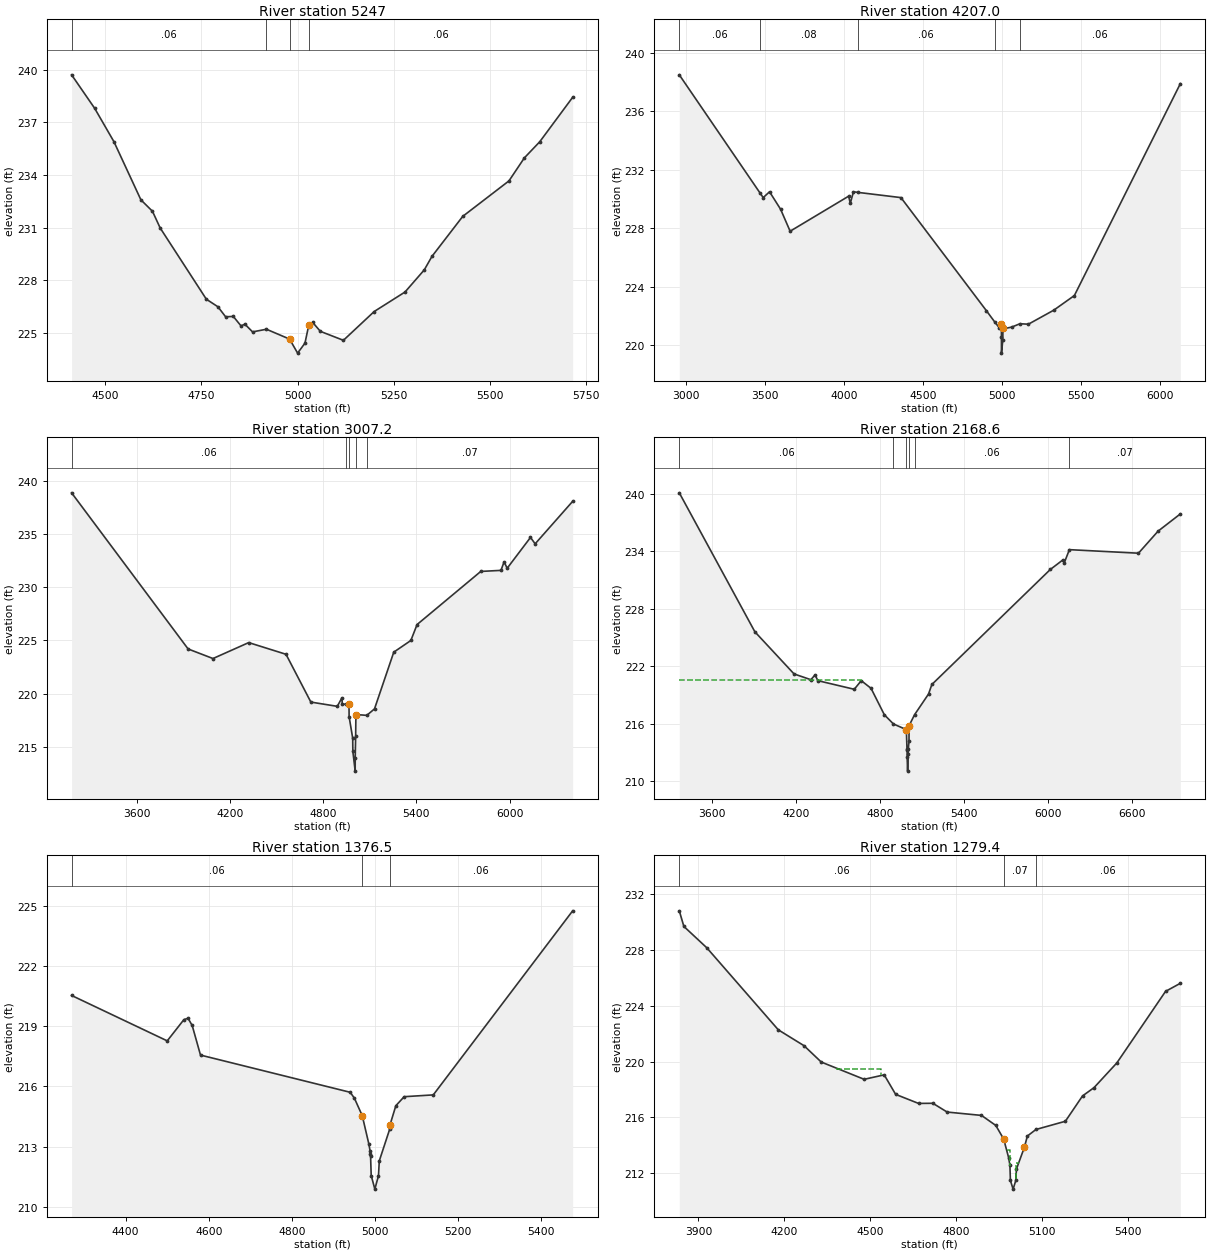
Type RM Length L Ch R = 1 ,5247    ,1075,1040,855
BEGIN DESCRIPTION:
Cross Section K166-03-00-X05
END DESCRIPTION:
XS GIS Cut Line= 4
      2945579.09      13937709.4      2945164.06      13937942.7
      2944987.24      13938089.5      2944715.91      13938619.4
#Sta/Elev= 30
    4413   239.7    4473  237.79    4523  235.89    4593  232.58    4623  231.93
    4643  230.98    4763  226.92    4793  226.49    4813  225.92    4833  225.94
    4853   225.4    4863   225.5    4883  225.06  4919.1  225.21  4979.1  224.65
    5000  223.85  5019.1  224.42  5029.1  225.46  5039.1   225.6  5059.1  225.09
  5118.9  224.58  5198.9  226.22  5278.9  227.33  5328.9  228.59  5348.9  229.36
  5428.9  231.64  5548.9  233.66  5588.9  234.97  5628.9  235.89  5714.3  238.42
#Mann= 4 ,-1 , 0
    4413     .06       0  4919.1     .05       0  4979.1     .05       0
  5029.1     .06       0
Bank Sta=4979.1,5029.1
XS Rating Curve= 0
Exp/Cntr=.3,.1

Type RM Length L Ch R = 1 ,4207.0  ,1005,1199.8,1340
BEGIN DESCRIPTION:
Cross Section K166-03-00-X04
Changed bank stations from 4953.9 to 4994.5 and 5112.4 to  5004.8. - JJA 3/19/03
END DESCRIPTION:
XS GIS Cut Line= 4
      2945167.15      13935582.2      2944294.06     13937337.64
        2944259.     13937559.67      2944307.77     13938537.92
#Sta/Elev= 27
  2960.8   238.5  3471.7   230.4  3490.8   230.1  3530.8   230.5  3600.8   229.3
  3660.8   227.8  4030.8   230.2  4040.8   229.7  4060.8   230.5  4087.1  230.46
  4360.8   230.1  4900.7  222.36  4953.9  221.58  4982.1  221.19  4994.5  221.47
  4995.2  221.25  4995.5  220.58  4995.7  219.46  5004.1  220.35  5004.8  221.18
  5005.2  221.12  5060.1  221.24  5112.4  221.47  5165.9  221.44  5326.2   222.4
  5456.2   223.4  6125.6   237.9
#Mann= 5 ,-1 , 0
  2960.8     .06       0  3471.7     .08       0  4087.1     .06       0
  4953.9     .05       0  5112.4     .06       0
Bank Sta=4994.5,5004.8
XS Rating Curve= 0
Exp/Cntr=.3,.1

Type RM Length L Ch R = 1 ,3007.2  ,750,838.6,815
BEGIN DESCRIPTION:
Cross Section K166-03-00-X03
END DESCRIPTION:
XS GIS Cut Line= 4
      2944633.29     13935295.74      2943584.24     13936700.44
      2943425.44     13936785.95      2942654.13     13937821.78
#Sta/Elev= 30
  3181.4   238.9  3931.4   224.2  4091.4   223.3  4321.4   224.8  4561.4   223.7
  4721.4   219.2  4891.4   218.8  4921.4   219.6  4923.7  218.98  4950.3  219.02
  4966.9  219.05  4967.5  217.83  4990.7   215.8  4991.7  214.55  5006.7   212.7
  5006.8  213.94  5009.7  215.98  5011.3  218.03  5081.4  217.95    5131  218.56
    5255   223.9    5365     225    5405   226.5    5815   231.5    5945   231.6
    5965   232.4    5985   231.8    6135   234.7    6165   234.1  6406.4   238.1
#Mann= 5 ,-1 , 0
  3181.4     .06       0  4950.3      .1       0  4966.9     .08       0
  5011.3      .1       0  5081.4     .07       0
Bank Sta=4966.9,5011.3
XS Rating Curve= 0
Exp/Cntr=.3,.1

Type RM Length L Ch R = 1 ,2168.6  ,730,792.1,716
BEGIN DESCRIPTION:
Cross Section K166-03-00-X02
Changed reach lengths from 901.8 to 871.59 and  843. - JJA 3/19/03
END DESCRIPTION:
XS GIS Cut Line= 5
      2944477.04     13935165.53      2943149.83     13936041.87
       2942945.3     13936105.24      2942654.13     13936506.67
      2942562.98     13937782.72
#Sta/Elev= 30
  3368.2   240.1  3908.2   225.6  4188.2   221.2  4308.2   220.6  4338.2   221.1
  4358.2   220.5  4618.2   219.6  4668.2   220.5  4738.2   219.7  4833.2  216.94
  4898.2  215.98  4990.4  215.39  4995.1  213.27    4996  213.32  4996.1   212.5
  4999.4  211.06    5004  212.88  5004.1  213.32  5009.4  214.23  5009.5  215.79
  5049.2  216.95    5149  219.11  5172.7   220.1  6018.7   232.1  6108.7   233.1
  6118.7   232.8  6155.2  234.17  6648.7   233.8  6788.7   236.1    6948   237.9
#Mann= 6 ,-1 , 0
  3368.2     .06       0  4898.2     .07       0  4990.4     .07       0
  5009.5     .07       0  5049.2     .06       0  6155.2     .07       0
#XS Ineff= 2 , 0
         4668.22  220.52
Permanent Ineff=
       F       F
Bank Sta=4990.4,5009.5
XS Rating Curve= 0
Exp/Cntr=.3,.1

Type RM Length L Ch R = 1 ,1376.5  ,95,97.1,84
BEGIN DESCRIPTION:
S2_Private Bridge - XS 4
LIDAR overbanks, Interpolated channel
END DESCRIPTION:
XS GIS Cut Line= 3
      2943693.15     13935091.63      2942942.45     13935302.57
      2942722.67     13935666.56
#Sta/Elev= 23
  4270.3  220.55  4500.3  218.28  4540.3  219.34  4550.3  219.41  4560.3  219.05
  4580.3  217.57  4940.3  215.71  4950.3  215.42 4969.29  214.54 4985.12  213.13
 4988.14  212.78 4988.47  212.65 4989.27  212.54 4990.83  211.55 4999.58  210.87
 5008.31  211.54 5010.24  212.28 5035.51  213.88 5035.87  214.07  5050.1  215.04
  5070.1  215.49  5140.1  215.58  5475.3  224.78
#Mann= 3 ,-1 , 0
  4270.3     .06       0 4969.29     .07       0 5035.51     .06       0
Bank Sta=4969.29,5035.87
XS Rating Curve= 0
Exp/Cntr=.5,.3

Type RM Length L Ch R = 1 ,1279.4  ,30,30.8,40
BEGIN DESCRIPTION:
S2_Private Bridge - XS 3
END DESCRIPTION:
XS GIS Cut Line= 4
 2944119.374298113934876.2037717      2942982.81     13935186.96
       2942905.7     13935217.24 2942652.535742313935636.5186962
#Sta/Elev= 30
  3833.1  230.82  3849.1   229.7  3929.1  228.17  4179.1  222.28  4269.1  221.14
  4329.1  219.97  4479.1  218.73  4549.1  219.05  4589.1  217.65  4669.1     217
  4719.1  217.01  4769.1  216.38  4889.1  216.14  4939.1  215.42  4966.7  214.44
    4984   213.1  4988.4  212.56  4990.1  211.47  4999.6  210.85  5009.1  211.48
  5011.2  212.29  5039.1  213.86  5049.4  214.66  5079.4  215.13  5182.2  215.72
  5242.2  217.54  5282.2  218.13  5362.2  219.91  5532.2  225.04    5584  225.62
#Mann= 3 ,-1 , 0
  3833.1     .06       0  4966.7     .07       0  5079.4     .06       0
#XS Ineff= 3 ,-1
 4382.03 4539.17   219.5 4977.14  4988.5  213.64  5009.3 5020.82  212.74
Permanent Ineff=
       F       F       F
Bank Sta=4966.7,5039.1
XS Rating Curve= 0
Exp/Cntr=.5,.3

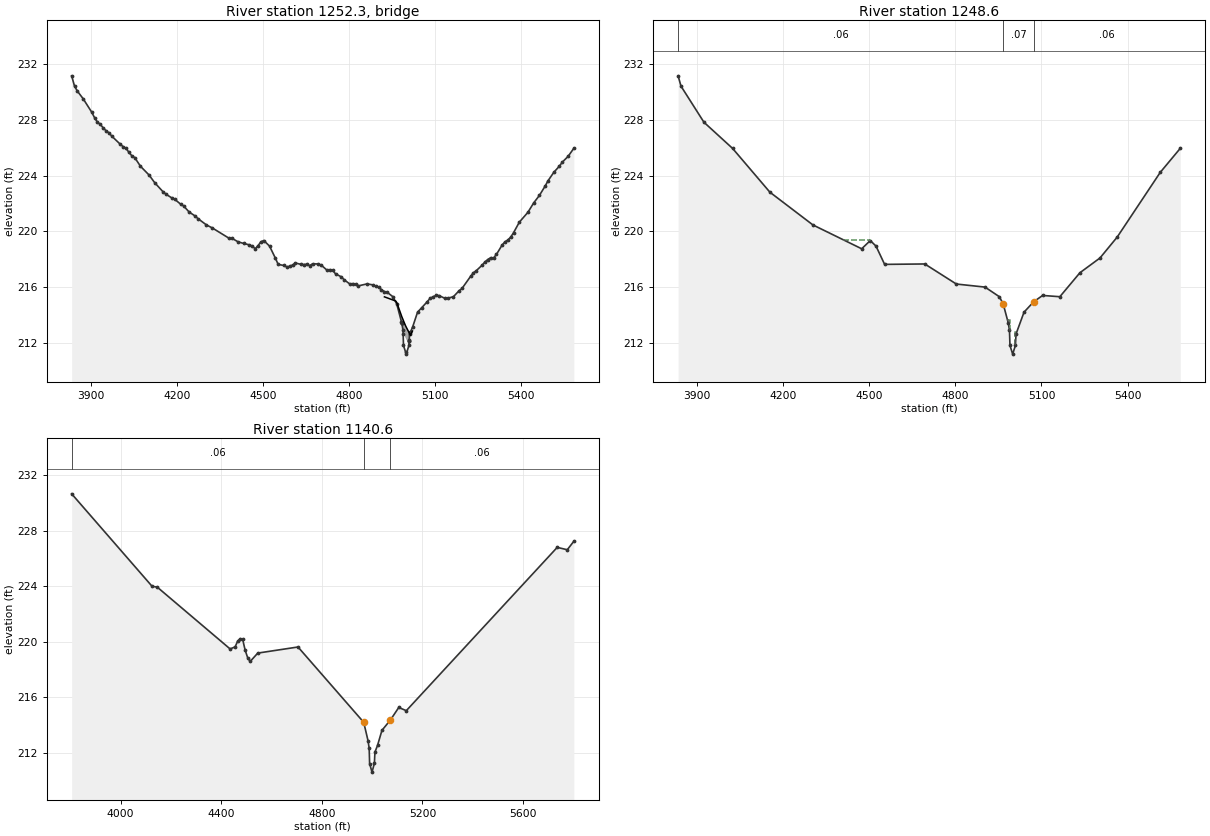
Type RM Length L Ch R = 3 ,1252.3  ,,,
BEGIN DESCRIPTION:
PRIVATE BRIDGE 1250' US K166-00-00
Structure ID: K166-03-00-S2
END DESCRIPTION:
Bridge Culvert--1,0,-1,-1, 0
Deck Dist Width WeirC Skew NumUp NumDn MinLoCord MaxHiCord MaxSubmerge Is_Ogee
10,9,2.6,0, 18, 18, , , .95, 0, 1,1,,
  4923.6  4963.1  4966.7    4984 4984.11  4984.3  4988.4  4988.8  4990.1  4997.2
  4999.6  5009.1 5009.87 5009.99  5010.1  5011.2  5014.2  5021.5
   215.3     215  214.89  213.89  213.88  213.87  213.67  213.65  213.58  213.23
  213.13  212.75  212.72  212.71  212.71  212.66  212.54  212.85
  215.12  214.51  214.45  213.11  213.09  213.07   212.8  212.78  212.71  212.36
  212.26  211.88  211.85  211.84  211.88   212.3  212.44  212.78
  4923.6  4963.1  4966.7    4984 4984.11  4984.3  4988.4  4988.8  4990.1  4997.2
  4999.6  5009.1 5009.87 5009.99  5010.1  5011.2  5014.2  5021.5
   215.3     215  214.89  213.89  213.88  213.87  213.67  213.65  213.58  213.23
  213.13  212.75  212.72  212.71  212.71  212.66  212.54  212.85
  215.12  214.51  214.45  213.11  213.09  213.07   212.8  212.78  212.71  212.36
  212.26  211.88  211.85  211.84  211.88   212.3  212.44  212.78
BR Coef= 1 , 1 , 0 ,1.25, 0 ,,,.8,0,2,0,
WSPro=,,,, 1 ,,,, 0 ,,,, 0 ,,,,-1 ,-1 ,-1 , 0 , 0 , 0 , 0 , 0
BR U #Sta/Elev= 131
  3833.1  231.16  3843.1  230.42  3853.1  230.06  3873.1  229.52  3903.1  228.55
  3913.1  228.15  3923.1  227.83  3933.1  227.68  3943.1  227.42  3953.1  227.22
  3963.1  227.07  3973.1  226.83  4003.1  226.24  4013.1  226.07  4023.1  225.95
  4033.1  225.66  4043.1  225.42  4053.1  225.29  4073.1  224.67  4103.1  224.04
  4123.1  223.48  4153.1  222.81  4163.1  222.65  4183.1  222.39  4193.1  222.29
  4213.1  221.95  4223.1  221.83  4243.1  221.38  4263.1  221.11  4273.1  220.92
  4303.1  220.46  4323.1  220.25  4383.1  219.49  4393.1  219.49  4413.1  219.25
  4433.1  219.13  4453.1  219.03  4463.1  218.94  4473.1  218.75  4483.1  218.98
  4493.1  219.25  4503.1  219.34  4523.1  218.94  4543.1  218.09  4553.1  217.63
  4573.1  217.55  4583.1  217.45  4593.1  217.49  4603.1  217.58  4613.1  217.73
  4633.1  217.63  4643.1  217.62  4653.1  217.64  4663.1  217.54  4673.1  217.67
  4693.1  217.66  4703.1  217.58  4723.1  217.22  4733.1  217.25  4743.1  217.21
  4753.1  216.95  4773.1  216.74  4783.1  216.53  4803.1  216.22  4813.1  216.25
  4823.1   216.2  4833.1  216.09  4863.1  216.23  4883.1  216.16  4893.1  216.05
  4903.1     216  4913.1  215.82  4923.1  215.68  4933.1  215.63  4953.1  215.31
  4966.7  214.78  4983.1  213.51  4983.9  213.45    4984  213.44 4984.11  213.42
  4984.2  213.41  4984.3   213.4  4988.4   212.9  4988.8   212.6  4990.1  211.81
  4997.2  211.35  4999.6  211.19  5009.1  211.82 5009.87  212.12 5009.99  212.16
  5010.1  212.21  5011.2  212.63  5014.2  212.77  5021.5  213.11  5039.1   214.2
  5053.1  214.51  5072.9  214.95  5083.1   215.2    5094  215.31    5104   215.4
    5114  215.39    5134   215.2    5144   215.2    5164  215.31    5184  215.74
    5194   215.9    5224  216.77    5234  217.03    5244  217.18    5264  217.57
    5274   217.8    5284  217.98    5294  218.11    5304  218.09    5314  218.34
    5334  219.02    5344  219.25    5354  219.38    5364  219.59    5374  219.91
    5394  220.66    5424  221.37    5444  222.04    5464  222.58    5484  223.25
    5494  223.63    5514  224.23    5534  224.69    5544  224.97    5564  225.38
    5584  225.96
BR U #Mann= 3
  3833.1     .06  4966.7     .07  5072.9     .06
BR U Banks=4966.7,5039.1
BR D #Sta/Elev= 131
  3833.1  231.16  3843.1  230.42  3853.1  230.06  3873.1  229.52  3903.1  228.55
  3913.1  228.15  3923.1  227.83  3933.1  227.68  3943.1  227.42  3953.1  227.22
  3963.1  227.07  3973.1  226.83  4003.1  226.24  4013.1  226.07  4023.1  225.95
  4033.1  225.66  4043.1  225.42  4053.1  225.29  4073.1  224.67  4103.1  224.04
  4123.1  223.48  4153.1  222.81  4163.1  222.65  4183.1  222.39  4193.1  222.29
  4213.1  221.95  4223.1  221.83  4243.1  221.38  4263.1  221.11  4273.1  220.92
  4303.1  220.46  4323.1  220.25  4383.1  219.49  4393.1  219.49  4413.1  219.25
  4433.1  219.13  4453.1  219.03  4463.1  218.94  4473.1  218.75  4483.1  218.98
  4493.1  219.25  4503.1  219.34  4523.1  218.94  4543.1  218.09  4553.1  217.63
  4573.1  217.55  4583.1  217.45  4593.1  217.49  4603.1  217.58  4613.1  217.73
  4633.1  217.63  4643.1  217.62  4653.1  217.64  4663.1  217.54  4673.1  217.67
  4693.1  217.66  4703.1  217.58  4723.1  217.22  4733.1  217.25  4743.1  217.21
  4753.1  216.95  4773.1  216.74  4783.1  216.53  4803.1  216.22  4813.1  216.25
  4823.1   216.2  4833.1  216.09  4863.1  216.23  4883.1  216.16  4893.1  216.05
  4903.1     216  4913.1  215.82  4923.1  215.68  4933.1  215.63  4953.1  215.31
  4966.7  214.78  4983.1  213.51  4983.9  213.45    4984  213.44 4984.11  213.42
  4984.2  213.41  4984.3   213.4  4988.4   212.9  4988.8   212.6  4990.1  211.81
  4997.2  211.35  4999.6  211.19  5009.1  211.82 5009.87  212.12 5009.99  212.16
  5010.1  212.21  5011.2  212.63  5014.2  212.77  5021.5  213.11  5039.1   214.2
  5053.1  214.51  5072.9  214.95  5083.1   215.2    5094  215.31    5104   215.4
    5114  215.39    5134   215.2    5144   215.2    5164  215.31    5184  215.74
    5194   215.9    5224  216.77    5234  217.03    5244  217.18    5264  217.57
    5274   217.8    5284  217.98    5294  218.11    5304  218.09    5314  218.34
    5334  219.02    5344  219.25    5354  219.38    5364  219.59    5374  219.91
    5394  220.66    5424  221.37    5444  222.04    5464  222.58    5484  223.25
    5494  223.63    5514  224.23    5534  224.69    5544  224.97    5564  225.38
    5584  225.96
BR D #Mann= 3
  3833.1     .06  4966.7     .07  5072.9     .06
BR D Banks=4966.7,5039.1
BC Design=,, 0 ,, 0 ,,,,,,
BC HTab HWMax=230.82

Type RM Length L Ch R = 1 ,1248.6  ,105,107,102
BEGIN DESCRIPTION:
S2_Private Bridge - XS 2
END DESCRIPTION:
XS GIS Cut Line= 4
 2944107.452022913934847.9878016      2942968.63     13935159.36
      2942893.35     13935188.92 2942640.364397713935607.8959494
#Sta/Elev= 30
  3833.1  231.16  3843.1  230.42  3923.1  227.83  4023.1  225.95  4153.1  222.81
  4303.1  220.46  4473.1  218.75  4503.1  219.34  4523.1  218.94  4553.1  217.63
  4693.1  217.66  4803.1  216.22  4903.1     216  4953.1  215.31  4966.7  214.78
    4984  213.44  4988.4   212.9  4990.1  211.81  4999.6  211.19  5009.1  211.82
  5011.2  212.63  5039.1   214.2  5072.9  214.95    5104   215.4    5164  215.31
    5234  217.03    5304  218.09    5364  219.59    5514  224.23    5584  225.96
#Mann= 3 ,-1 , 0
  3833.1     .06       0  4966.7     .07       0  5072.9     .06       0
#XS Ineff= 3 ,-1
  4406.8 4502.92  219.36 4981.36 4988.56  213.66 5009.24  5013.7  212.75
Permanent Ineff=
       F       F       F
Bank Sta=4966.7,5072.9
XS Rating Curve= 0
Exp/Cntr=.5,.3

Type RM Length L Ch R = 1 ,1140.6  ,0,0,0
BEGIN DESCRIPTION:
S2_Private Bridge - XS 1
END DESCRIPTION:
XS GIS Cut Line= 3
       2944080.4       13934751.      2942828.21     13935103.34
      2942468.44     13935699.18
#Sta/Elev= 28
  3805.4  230.66  4125.4  223.99  4145.4  223.94  4435.4  219.48  4455.4  219.63
  4465.4  220.04  4475.4  220.22  4485.4  220.16  4495.4  219.38  4505.4  218.84
  4515.4  218.58  4545.4  219.18  4705.4  219.62  4966.7  214.19    4984  212.85
  4988.4  212.31  4990.1  211.22  4999.6   210.6  5009.1  211.23  5011.2  212.04
  5021.5  212.52  5039.1  213.61  5072.9  214.36    5106  215.26    5136  215.03
    5736   226.8    5776  226.63  5802.1  227.24
#Mann= 3 ,-1 , 0
  3805.4     .06       0  4966.7     .07       0  5072.9     .06       0
Bank Sta=4966.7,5072.9
XS Rating Curve= 0
Exp/Cntr=.3,.1

Chan Stop Cuts=-1